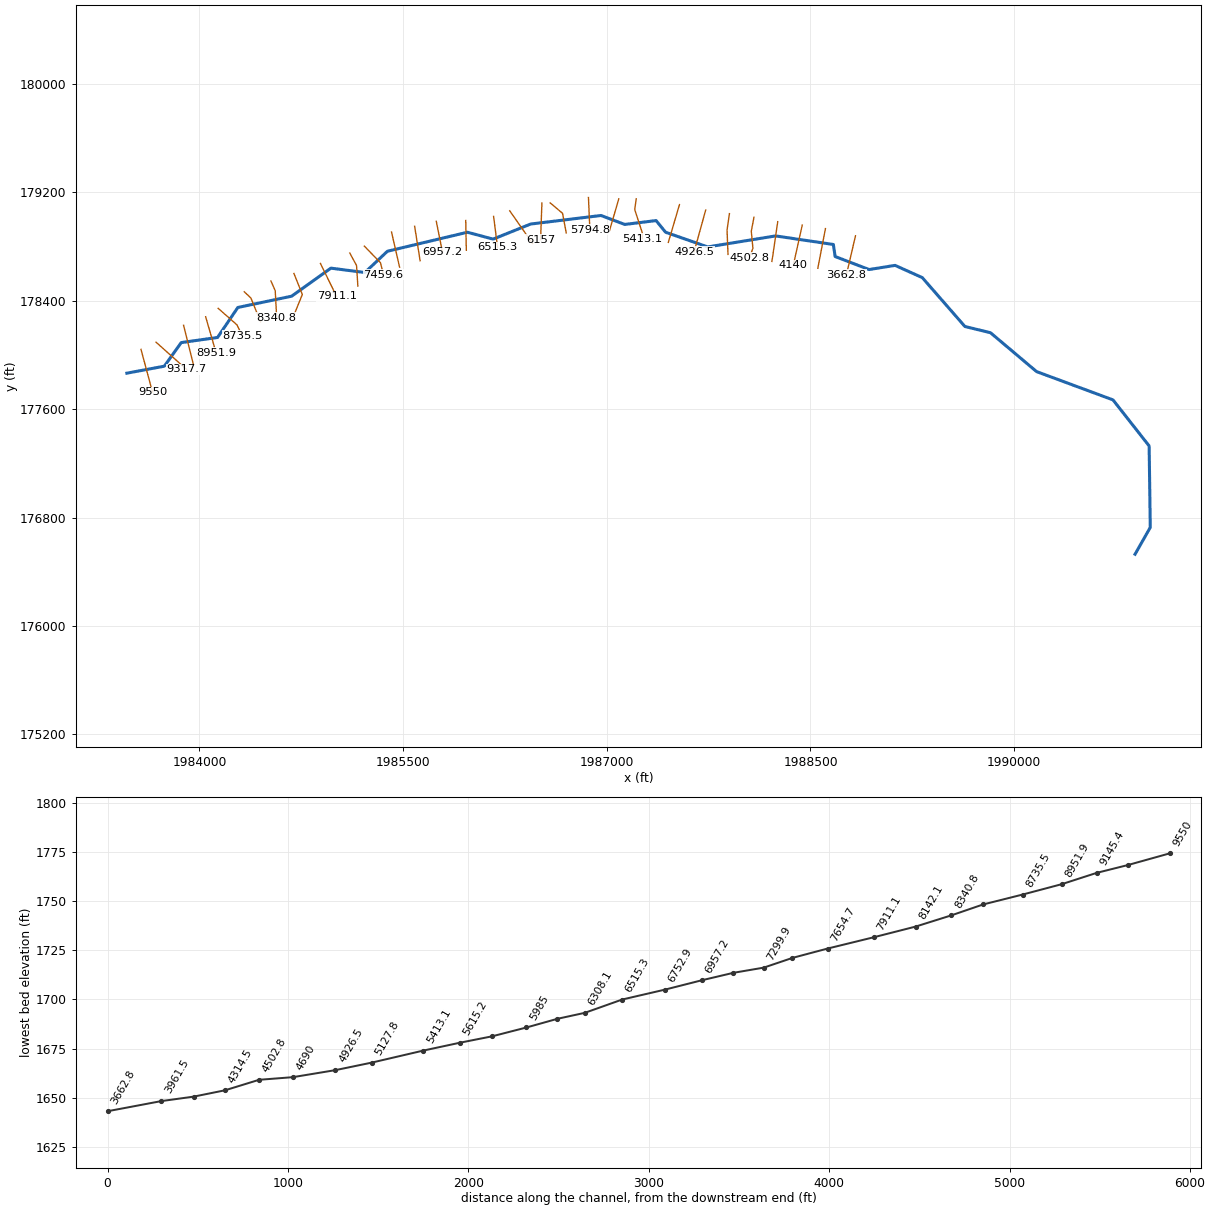
--- DRYFK.prj (project) ---

Proj Title=DRYFK
Current Plan=p01
Default Exp/Contr=0,0
English Units
Geom File=g01
Flow File=f01
Plan File=p01
BEGIN DESCRIPTION:
END DESCRIPTION:
DSS Export Rating Curves= 0
DSS Export Rating Curve Sorted= 0
DSS Export Volume Flow Curves= 0
DXF OffsetX= 0
DXF OffsetY= 0
DXF ScaleX= 0
DXF ScaleY= 0

--- DRYFK.p01 (plan) ---

Plan Title=Floodplain
Program Version=4.00
Geom File=g01
Flow File=f01
K Sum by GR=0
Std Step Tol=0.01
Critical Tol=0.01
Num of Std Step Trials=20
Max Error Tol=0.3
Flow Tol Ratio=0.001
Split Flow NTrial=30
Split Flow Tol=0.02
Split Flow Ratio=0.02
Log Output Level=0
Friction Slope Method=1
Unsteady Friction Slope Method=2
Unsteady Bridges Friction Slope Method=1
Global Log Level=0
CheckData=False
Run HTab=0
Run UNet=0
Run PostProcess=0
UNET Theta=0
UNET Theta Warmup=0
UNET ZTol=0
UNET ZSATol=0
UNET MxIter=0
UNET MaxInSteps=0
UNET DtIC=0
UNET DtMin=0
UNET MaxCRTS=0
UNET WFStab=0
UNET SFStab=0
UNET WFX=0
UNET SFX=0
UNET DSS MLevel=0
UNET DZMax Abort=0
UNET Convert EG Bridges=0
UNET Use Existing IB Tables=0
UNET Froude Limit=0
UNET Froude Power=0
Write IC File=0
Echo Input=False
Echo Output=False
Write Detailed=0

--- DRYFK.f01 (steady flow) ---

Flow Title=NFF Regression Equation
Program Version=4.10
Number of Profiles= 1
Profile Names=P100yr
River Rch & RM=DRYFK,Main            ,9550
 580.514
River Rch & RM=DRYFK,Main            ,9145.4
585.5541
River Rch & RM=DRYFK,Main            ,7911.1
650.2084
River Rch & RM=DRYFK,Main            ,6157
710.9622
River Rch & RM=DRYFK,Main            ,4314.5
 784.447
River Rch & RM=DRYFK,Main            ,1744.7
 867.674
River Rch & RM=DRYFK,Main            ,397.9
934.1937
River Rch & RM=DRYFK,Main            ,67.4
935.9212
Boundary for River Rch & Prof#=DRYFK,Main            , 1
Up Type= 0
Dn Type= 3
Dn Slope=0.011486
DSS Import GetInterval= 0
DSS Import GetPeak= 0
DSS Import FillOption= 0

--- DRYFK.g01 (geometry) ---

Geom Title=USGS 1m DEM
Program Version=4.10

River Reach=DRYFK           ,Main
Reach XY= 30
     1983465.518      177864.535     1983741.559      177916.098
     1983866.031      178090.126     1984133.613      178128.122
     1984282.937      178349.144     1984678.937      178432.269
     1984968.335      178639.234     1985218.353      178606.783
     1985384.326      178763.727     1985973.519      178903.994
     1986162.798       178853.31     1986439.187      178964.421
     1986957.242      179027.616     1987132.224      178961.456
     1987362.798      178990.116     1987432.937      178904.005
     1987743.353      178795.671     1988242.659      178876.922
     1988668.353      178813.727     1988681.548      178724.838
     1988931.548      178629.005     1989123.215       178659.56
     1989323.215      178569.283     1989637.103      178208.866
     1989825.298      178163.033     1990164.881      177876.227
     1990727.523      177667.579     1990993.816       177328.01
      1991002.15      176727.315     1990890.146      176529.261

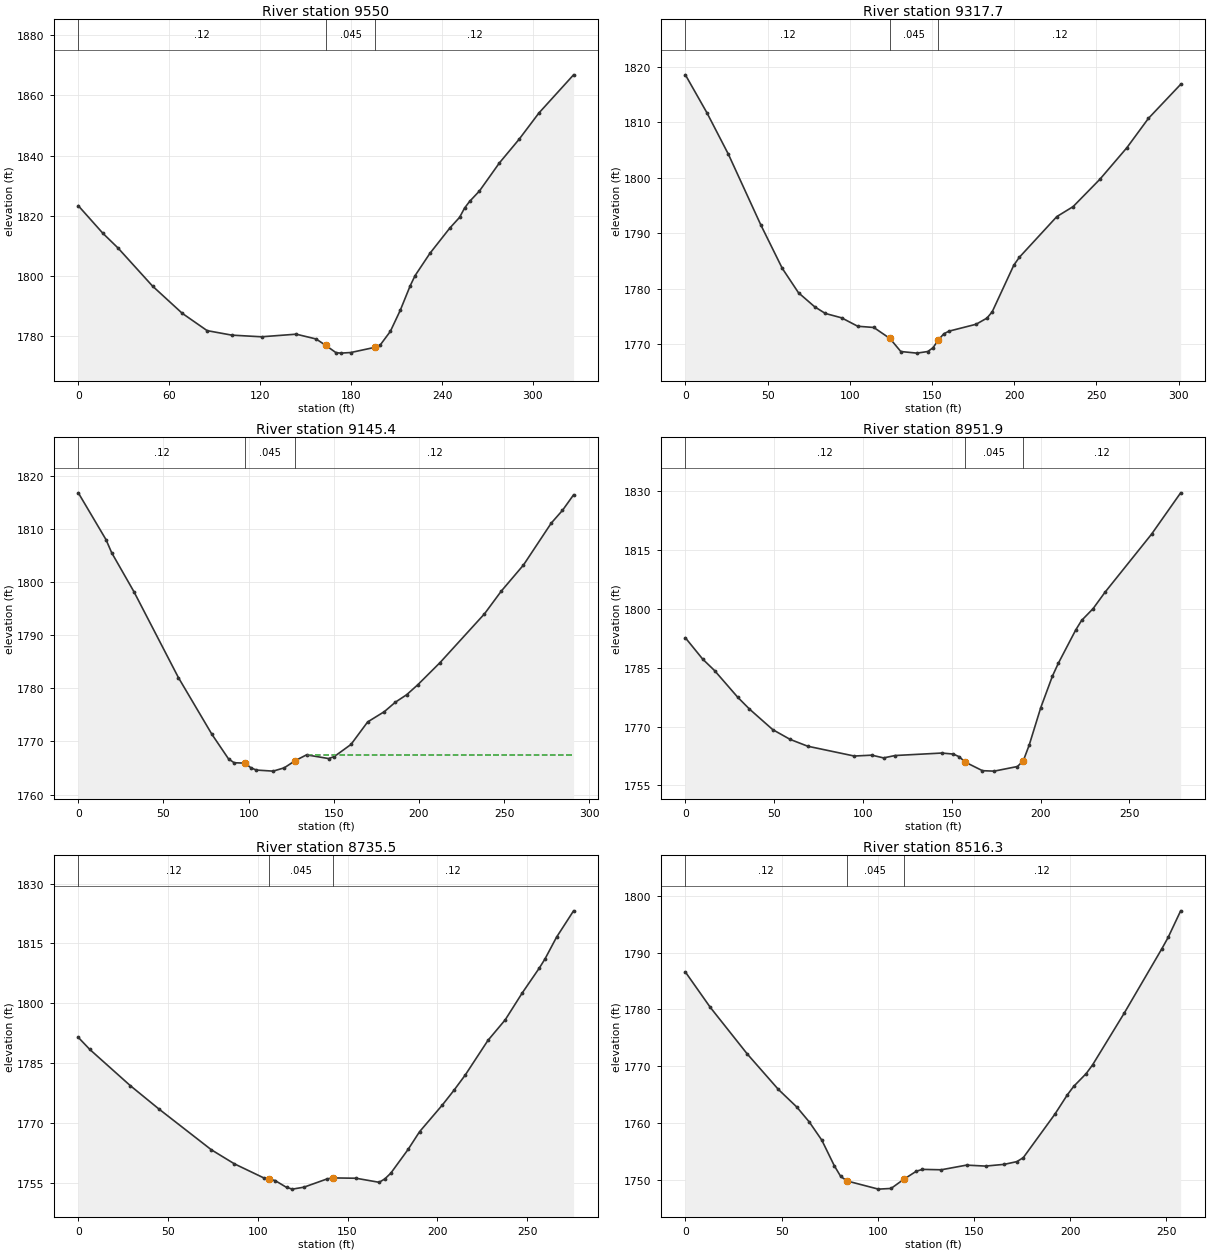
Type RM Length L Ch R = 1 ,9550    ,209.3,232.3,252
XS GIS Cut Line= 2
     1983569.629      178040.303     1983654.704      177724.751
#Sta/Elev= 30
       0 1823.33    16.3 1814.12    26.2 1809.28      49 1796.61    68.6 1787.56
      85 1781.81   101.3 1780.31   120.9 1779.76   143.8 1780.63   156.9 1779.03
   163.4 1776.87     170 1774.49   173.2 1774.33   179.8 1774.53   196.1  1776.3
   199.4 1777.15   205.9 1781.56   212.4 1788.52     219 1796.72   222.2 1800.08
     232 1807.49   245.1 1815.88   251.6 1819.47   254.9 1822.57   258.2 1824.76
   264.7 1828.23   277.8 1837.52   290.9 1845.44   303.9 1854.13   326.8 1866.84
#Mann= 3 ,-1 , 0
       0     .12       0   163.4    .045       0   196.1     .12       0
Bank Sta=163.4,196.1
XS Rating Curve= 0 ,0
Exp/Cntr=0.3,0.1

Type RM Length L Ch R = 1 ,9317.7  ,195.3,172.3,151.2
XS GIS Cut Line= 2
     1983680.378      178093.168     1983904.987       177892.43
#Sta/Elev= 30
       0  1818.6    13.1 1811.75    26.2 1804.24    45.8 1791.56    58.9 1783.69
    68.8 1779.27    78.6 1776.75    85.1 1775.54      95 1774.75   104.8 1773.23
   114.6 1773.01   124.4 1771.02     131 1768.67   140.8 1768.38   147.4 1768.67
   150.6 1769.35   153.9 1770.78   157.2 1771.88   160.4 1772.35   176.8 1773.59
   183.4  1774.7   186.6 1775.84   199.7 1784.23     203 1785.64   225.9 1793.02
   235.8 1794.82   252.1 1799.76   268.5 1805.45   281.6 1810.74   301.2 1816.88
#Mann= 3 ,-1 , 0
       0     .12       0   124.4    .045       0   153.9     .12       0
Bank Sta=124.4,153.9
XS Rating Curve= 0 ,0
Exp/Cntr=0.3,0.1

Type RM Length L Ch R = 1 ,9145.4  ,191.3,193.5,194.7
XS GIS Cut Line= 2
     1983883.286      178217.951     1983953.815      177935.833
#Sta/Elev= 30
       0  1816.9    16.3 1808.05    19.6  1805.6    32.7 1798.23    58.8 1782.04
    78.4 1771.38    88.2 1766.72    91.5 1765.99      98 1765.92   101.3 1765.04
   104.6 1764.61   114.4 1764.41   120.9 1765.03   127.4 1766.39     134 1767.48
     147 1766.78   150.3 1767.16   160.1 1769.44   169.9 1773.69   179.7 1775.63
   186.2 1777.42   192.8 1778.82   199.3 1780.69   212.4 1784.88   238.5 1794.08
   248.3 1798.34   261.4 1803.29   277.7 1811.19   284.3  1813.6   290.8 1816.52
#Mann= 3 ,-1 , 0
       0     .12       0      98    .045       0   127.4     .12       0
#XS Ineff= 2 , 0
                           134.3          1767.5
Permanent Ineff=
       F       F
Bank Sta=98,127.4
XS Rating Curve= 0 ,0
Exp/Cntr=0.3,0.1

Type RM Length L Ch R = 1 ,8951.9  ,193.5,216.4,238.4
XS GIS Cut Line= 2
     1984046.046      178280.885     1984123.086      178012.873
#Sta/Elev= 30
       0 1792.66     9.8  1787.2    16.4 1784.32    29.5 1777.49    36.1 1774.48
    49.2 1769.24      59 1766.75    68.9 1765.01    95.1 1762.51     105 1762.73
   111.6 1762.03   118.1 1762.64   144.4 1763.27   150.9 1763.01   154.2 1762.33
   157.5 1760.98   167.3 1758.77   173.9 1758.66     187 1759.84   190.3 1761.32
   193.6 1765.29   200.1 1774.82   206.7  1782.9     210 1786.15   219.8 1794.65
   223.1 1797.08   229.6  1800.1   236.2 1804.22   262.5 1819.08   278.9 1829.63
#Mann= 3 ,-1 , 0
       0     .12       0   157.5    .045       0   190.3     .12       0
Bank Sta=157.5,190.3
XS Rating Curve= 0 ,0
Exp/Cntr=0.3,0.1

Type RM Length L Ch R = 1 ,8735.5  ,232.8,219.3,200.9
XS GIS Cut Line= 3
     1984138.277      178342.734     1984276.081      178221.206
     1984317.314      178138.741
#Sta/Elev= 30
       0 1791.43     6.4 1788.41      29 1779.32    45.1 1773.41    74.1 1763.26
      87 1759.72   103.2 1756.23   106.4 1755.88   109.6 1755.55     116 1753.83
   119.3 1753.39   125.7 1753.88   138.6 1755.95   141.8  1756.2   154.7 1756.12
   167.6  1755.1   170.8 1755.97   174.1  1757.4   183.7 1763.33   190.1 1767.78
   202.8 1774.48   209.2 1778.13   215.5 1781.96   228.2 1790.68   237.8 1795.82
   247.3 1802.57   256.9 1808.87     260 1811.12   266.4 1816.54   275.9 1823.16
#Mann= 3 ,-1 , 0
       0     .12       0   106.4    .045       0   141.8     .12       0
Bank Sta=106.4,141.8
XS Rating Curve= 0 ,0
Exp/Cntr=0.3,0.1

Type RM Length L Ch R = 1 ,8516.3  ,193.5,175.5,161.8
XS GIS Cut Line= 3
     1984330.092      178465.177     1984379.163      178418.689
     1984450.777      178242.908
#Sta/Elev= 30
       0  1786.6    12.9 1780.39    32.2 1772.14    48.3 1765.92    57.9 1762.81
    64.4 1760.17    70.9 1756.97    77.4 1752.46    80.7 1750.59      84 1749.78
   100.3 1748.34   106.9 1748.46   113.4 1750.05     120 1751.49   123.2 1751.82
     133 1751.75   146.1 1752.57     156  1752.4   165.8 1752.71   172.3 1753.19
   175.6 1753.88     192 1761.53   198.5 1764.95   201.8 1766.44   208.3  1768.7
   211.6 1770.22     228 1779.31   247.6 1790.68   250.9  1792.7   257.4 1797.38
#Mann= 3 ,-1 , 0
       0     .12       0      84    .045       0   113.4     .12       0
Bank Sta=84,113.4
XS Rating Curve= 0 ,0
Exp/Cntr=0.3,0.1

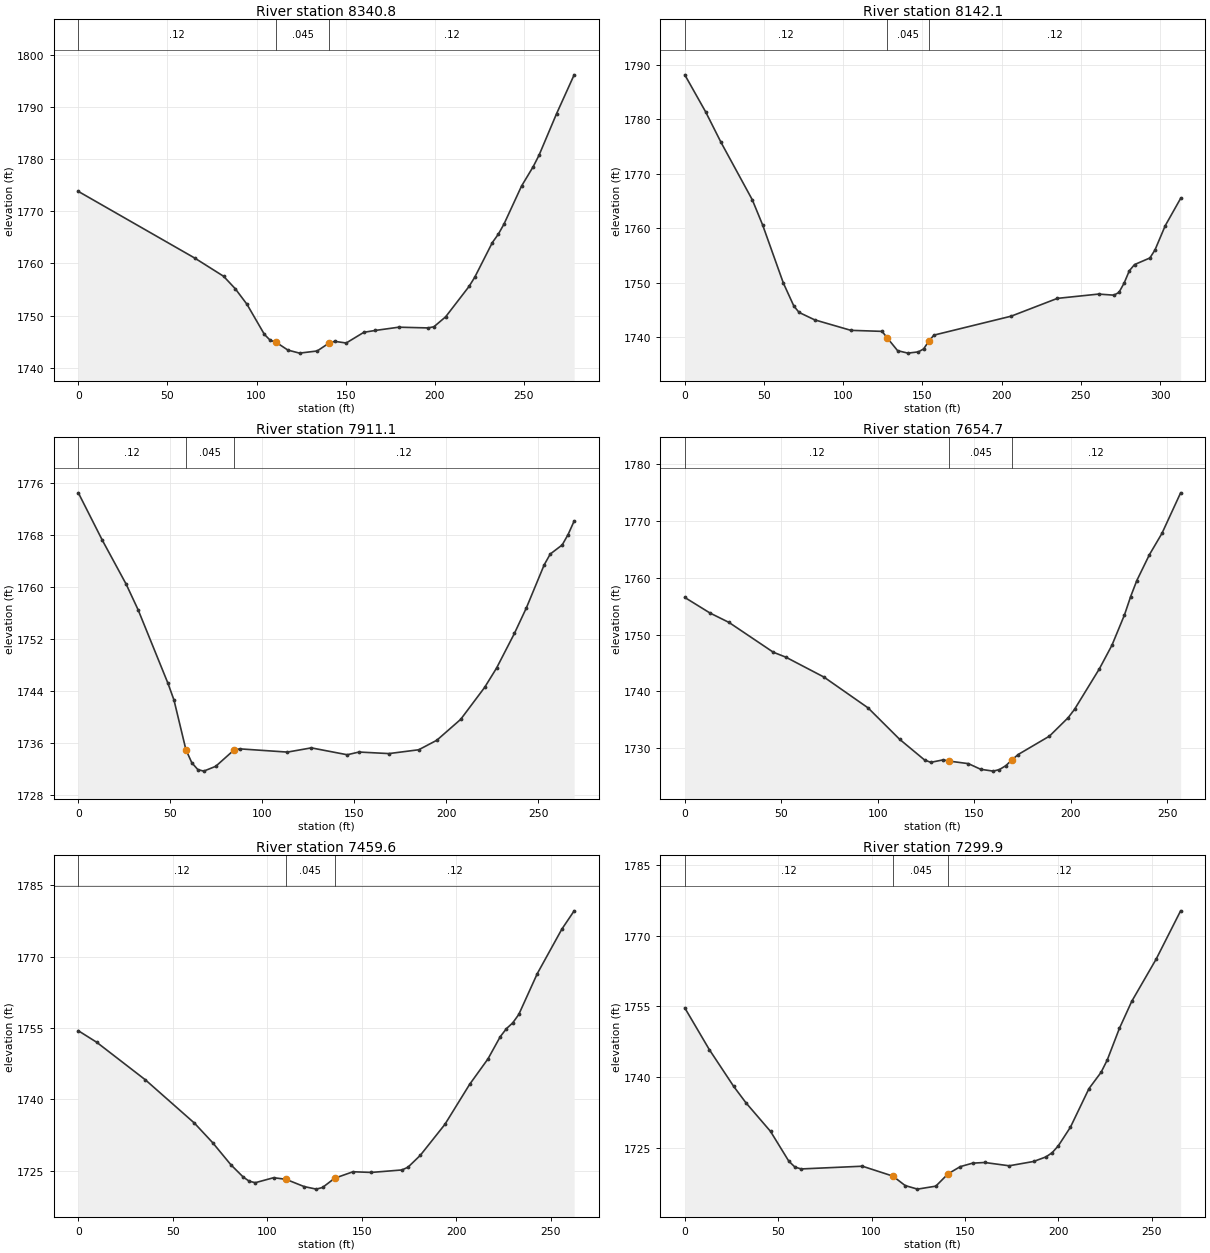
Type RM Length L Ch R = 1 ,8340.8  ,185.1,198.6,196.5
XS GIS Cut Line= 3
     1984526.732      178544.557     1984558.199      178472.942
      1984569.05       178273.29
#Sta/Elev= 30
       0  1773.8    65.2 1761.05    81.5 1757.54    88.1 1755.13    94.6 1752.18
   104.4  1746.4   107.7 1745.26     111 1744.88   117.6 1743.39   124.1 1742.81
     134 1743.22   140.5  1744.7   143.8 1745.07   150.3 1744.75   160.2  1746.8
   166.7 1747.16   179.8 1747.78   196.2 1747.64   199.5 1747.86   206.1 1749.77
   219.2 1755.58   222.4 1757.34   232.3    1764   235.6 1765.58   238.8 1767.52
   248.7 1774.84   255.2 1778.53   258.5 1780.74   268.3 1788.67   278.2 1796.14
#Mann= 3 ,-1 , 0
       0     .12       0     111    .045       0   140.5     .12       0
Bank Sta=111,140.5
XS Rating Curve= 0 ,0
Exp/Cntr=0.3,0.1

Type RM Length L Ch R = 1 ,8142.1  ,227.8,231,246.7
XS GIS Cut Line= 3
     1984696.003      178599.896     1984757.852      178444.731
     1984702.936      178309.554
#Sta/Elev= 30
       0 1788.12    13.1 1781.36    22.9 1775.71    42.6  1765.2    49.1  1760.6
    62.2 1749.93    68.8 1745.73    72.1 1744.55    81.9 1743.19   104.8 1741.26
   124.5 1741.07   127.7 1739.89   134.3 1737.53   140.8 1737.08   147.4 1737.31
   150.7 1737.85   153.9 1739.23   157.2 1740.38     206 1743.86   235.1 1747.12
   261.1 1747.91   270.8 1747.71     274 1748.22   277.3 1749.96   280.5 1752.17
   283.8 1753.32   293.5 1754.53   296.7 1755.99   303.2 1760.46   312.9 1765.46
#Mann= 3 ,-1 , 0
       0     .12       0   127.7    .045       0   153.9     .12       0
Bank Sta=127.7,153.9
XS Rating Curve= 0 ,0
Exp/Cntr=0.3,0.1

Type RM Length L Ch R = 1 ,7911.1  ,270.4,256.4,242.6
XS GIS Cut Line= 2
     1984891.315       178673.68     1985009.612      178431.444
#Sta/Elev= 30
       0 1774.51      13 1767.24      26 1760.45    32.5 1756.51    48.7 1745.21
      52 1742.62    58.5 1734.97    61.7 1732.96      65  1731.9    68.2 1731.67
    74.7 1732.41    84.4 1734.86    87.7  1735.1   113.7  1734.6   126.7 1735.25
   146.2 1734.19   152.6 1734.61   168.9 1734.37   185.1 1734.96   194.9 1736.42
   207.9 1739.64   220.9 1744.55   227.4 1747.53   237.1 1752.86   243.6 1756.79
   253.3 1763.42   256.6 1765.09   263.1 1766.49   266.3 1768.09   269.6 1770.17
#Mann= 3 ,-1 , 0
       0     .12       0    58.5    .045       0    84.4     .12       0
Bank Sta=58.5,84.4
XS Rating Curve= 0 ,0
Exp/Cntr=0.3,0.1

Type RM Length L Ch R = 1 ,7654.7  ,167.3,195.1,223.7
XS GIS Cut Line= 3
     1985107.244       178750.72     1985157.157      178658.489
     1985166.836      178506.681
#Sta/Elev= 30
       0 1756.53    13.1 1753.78    22.9 1752.13    45.9 1746.87    52.4    1746
    72.1  1742.5      95 1737.06   111.3 1731.54   124.3 1727.87   127.5 1727.46
     134  1727.9   137.2 1727.67     147 1727.23   153.4 1726.23   159.9 1725.91
   163.1 1726.19   166.4 1726.87   169.6 1727.91   172.8 1728.84     189 1732.08
   198.7 1735.33     202  1736.8   214.9 1743.96   221.4 1748.11   227.9 1753.46
   231.1 1756.69   234.3 1759.52   240.8 1764.06   247.3 1767.82     257 1774.98
#Mann= 3 ,-1 , 0
       0     .12       0   137.2    .045       0   169.6     .12       0
Bank Sta=137.2,169.6
XS Rating Curve= 0 ,0
Exp/Cntr=0.3,0.1

Type RM Length L Ch R = 1 ,7459.6  ,181.4,159.7,137.9
XS GIS Cut Line= 3
     1985214.666      178801.718     1985333.503      178678.556
     1985355.725       178590.13
#Sta/Elev= 30
       0 1754.44     9.7 1752.02    35.5 1744.11    61.4 1735.03      71 1730.94
    80.7 1726.27    87.2  1723.7    90.4 1722.82    93.6  1722.5   103.3 1723.55
   109.8 1723.22   119.5 1721.68   125.9 1721.15   129.2  1721.5   135.6 1723.44
   145.3  1724.8     155 1724.66   171.2 1725.18   174.4 1725.76   180.9 1728.25
   193.9 1734.75     207 1743.17   216.7 1748.52   223.2 1753.19   226.5 1754.89
   229.8 1756.09     233 1757.86   242.8 1766.45   255.8  1775.8   262.3 1779.64
#Mann= 3 ,-1 , 0
       0     .12       0   109.8    .045       0   135.6     .12       0
Bank Sta=109.8,135.6
XS Rating Curve= 0 ,0
Exp/Cntr=0.3,0.1

Type RM Length L Ch R = 1 ,7299.9  ,170.5,167.8,165.1
XS GIS Cut Line= 2
     1985414.833      178905.398     1985473.998      178646.554
#Sta/Elev= 30
       0 1754.69    13.1 1745.85    26.2    1738    32.8  1734.5    45.9 1728.45
    55.7 1722.12      59 1720.86    62.3 1720.47    95.1 1721.05   111.4 1718.95
     118 1716.94   124.6 1716.18   134.4 1716.81     141 1719.44   147.5 1720.96
   154.1  1721.7   160.6 1721.84   173.7 1721.14   186.8 1722.06   193.4 1723.03
   196.7 1723.92     200 1725.38   206.5 1729.35   216.4 1737.53   222.9    1741
   226.2 1743.61   232.7 1750.32   239.3 1756.07   252.4 1765.06   265.5 1775.32
#Mann= 3 ,-1 , 0
       0     .12       0   111.4    .045       0     141     .12       0
Bank Sta=111.4,141
XS Rating Curve= 0 ,0
Exp/Cntr=0.3,0.1

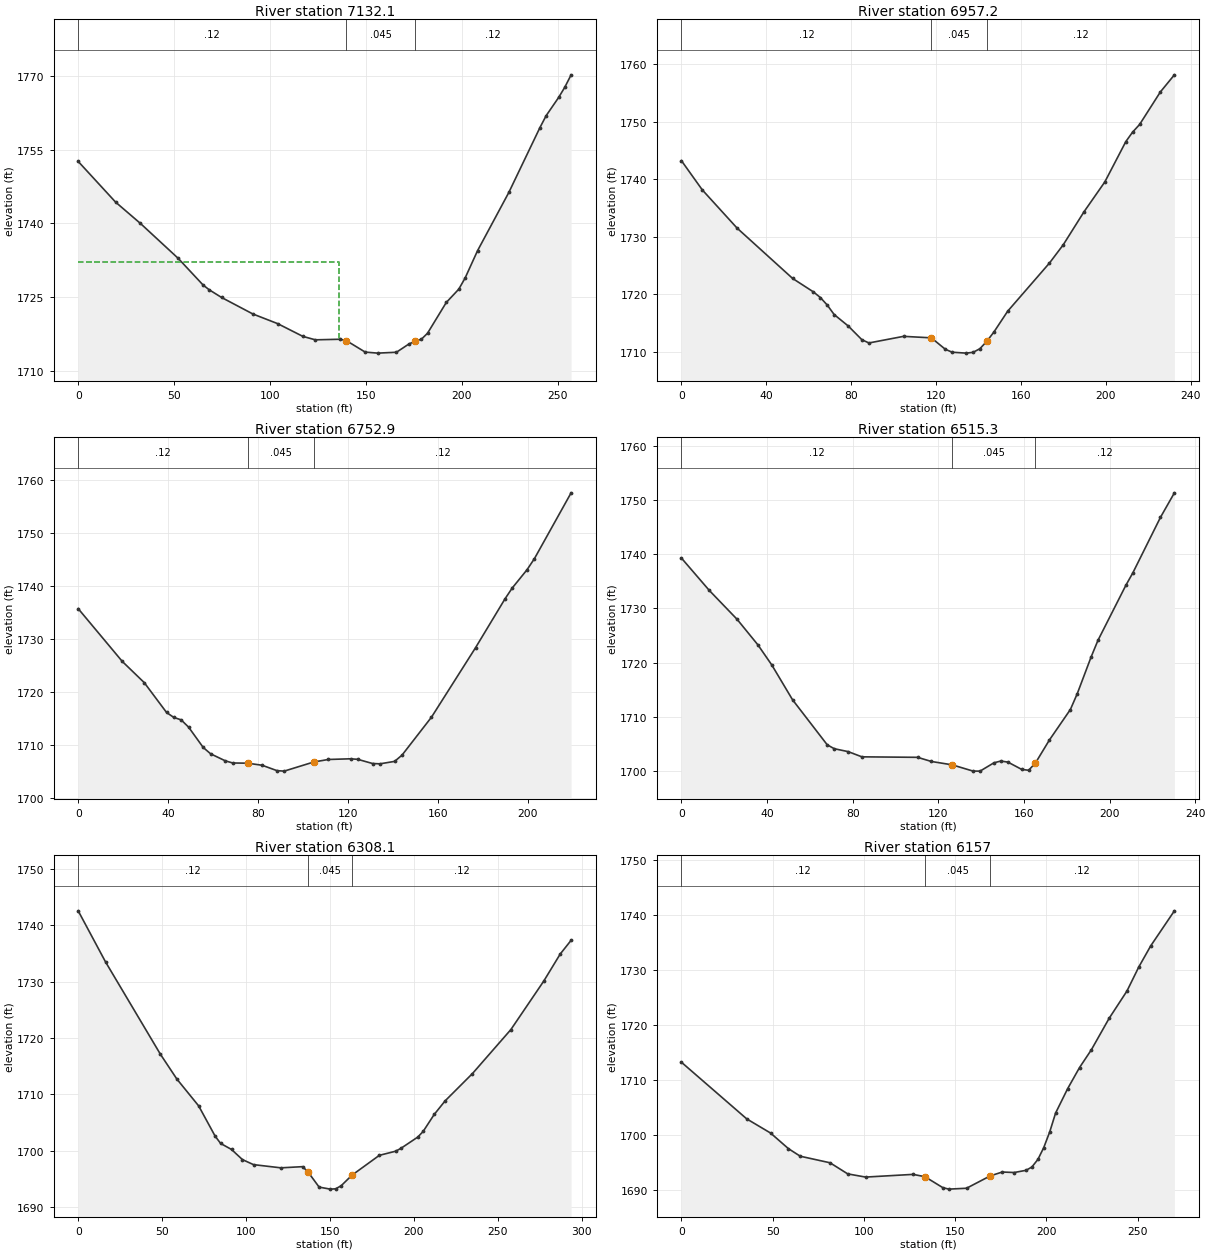
Type RM Length L Ch R = 1 ,7132.1  ,173.2,174.9,176.4
XS GIS Cut Line= 2
     1985584.805      178948.087      1985625.17      178694.181
#Sta/Elev= 30
       0 1752.62    19.5 1744.33    32.5 1739.97    52.1 1732.89    65.1 1727.45
    68.3 1726.47    74.8 1724.89    91.1 1721.53   104.1 1719.55   117.2 1716.96
   123.7 1716.26   136.7 1716.38   139.9 1716.09   149.7 1713.76   156.2 1713.55
     166 1713.73   172.5 1715.41   175.7 1715.98     179 1716.38   182.2  1717.6
     192 1723.88   198.5 1726.58   201.8 1728.85   208.3 1734.43   224.6 1746.29
   240.8 1759.49   244.1 1761.96   250.6 1765.66   253.8 1767.74   257.1 1770.27
#Mann= 3 ,-1 , 0
       0     .12       0   139.9    .045       0   175.7     .12       0
#XS Ineff= 2 , 0
          135.81 1732.14
Permanent Ineff=
       F       F
Bank Sta=139.9,175.7
XS Rating Curve= 0 ,0
Exp/Cntr=0.3,0.1

Type RM Length L Ch R = 1 ,6957.2  ,211.3,204.3,196.5
XS GIS Cut Line= 2
      1985744.18      178985.095     1985789.753      178757.231
#Sta/Elev= 30
       0 1743.25     9.8 1738.18    26.2 1731.53    52.4 1722.76    62.2 1720.42
    65.5 1719.43    68.7 1718.14      72 1716.47    78.6 1714.49    85.1 1712.08
    88.4 1711.53   104.7 1712.68   117.8 1712.42   124.4 1710.43   127.6 1709.92
   134.2 1709.76   137.5  1709.9   140.7 1710.53     144 1711.84   147.3 1713.43
   153.8 1717.06   173.5 1725.44     180 1728.62   189.8 1734.37   199.6 1739.56
   209.5 1746.58   212.7 1748.23     216 1749.56   225.8 1755.23   232.4  1758.2
#Mann= 3 ,-1 , 0
       0     .12       0   117.8    .045       0     144     .12       0
Bank Sta=117.8,144
XS Rating Curve= 0 ,0
Exp/Cntr=0.3,0.1

Type RM Length L Ch R = 1 ,6752.9  ,233.1,237.6,241.8
XS GIS Cut Line= 2
     1985961.194      178990.521     1985965.534      178771.336
#Sta/Elev= 30
       0  1735.7    19.6 1725.73    29.4 1721.71    39.3 1716.08    42.5 1715.15
    45.8 1714.68    49.1 1713.31    55.6 1709.47    58.9 1708.27    65.4 1706.95
    68.7 1706.54    75.3  1706.5    81.8 1706.11    88.4 1705.09    91.6    1705
   104.7 1706.72   111.2  1707.2   121.1 1707.33   124.3 1707.23   130.9 1706.44
   134.2 1706.38   140.7 1706.84     144 1708.02   157.1 1715.19   176.7 1728.32
   189.8 1737.55     193 1739.59   199.6 1743.05   202.9 1745.16   219.2 1757.58
#Mann= 3 ,-1 , 0
       0     .12       0    75.3    .045       0   104.7     .12       0
Bank Sta=75.3,104.7
XS Rating Curve= 0 ,0
Exp/Cntr=0.3,0.1

Type RM Length L Ch R = 1 ,6515.3  ,187.6,207.3,226.2
XS GIS Cut Line= 2
     1986166.446      179020.526     1986195.612      178792.054
#Sta/Elev= 30
       0 1739.29      13 1733.32      26 1727.98    35.7 1723.27    42.2 1719.55
    51.9 1713.12    68.1  1704.8    71.4 1704.08    77.9 1703.54    84.3 1702.58
   110.3 1702.49   116.8 1701.72   126.5  1701.1   136.2 1699.95   139.5 1699.94
     146 1701.48   149.2  1701.8   152.5 1701.61     159 1700.25   162.2  1700.1
   165.4 1701.45   171.9 1705.69   181.7 1711.32   184.9 1714.23   191.4 1721.04
   194.6 1724.11   207.6 1734.25   210.9 1736.58   223.8 1746.83   230.3 1751.35
#Mann= 3 ,-1 , 0
       0     .12       0   126.5    .045       0   165.4     .12       0
Bank Sta=126.5,165.4
XS Rating Curve= 0 ,0
Exp/Cntr=0.3,0.1

Type RM Length L Ch R = 1 ,6308.1  ,177,151.1,125
XS GIS Cut Line= 2
     1986285.065      179062.222     1986453.251      178821.336
#Sta/Elev= 30
       0 1742.58    16.3 1733.51      49 1717.12    58.8 1712.72    71.8 1707.95
    81.6 1702.59    84.9 1701.28    91.4 1700.21    97.9 1698.41   104.5 1697.52
   120.8 1696.95   133.8 1697.16   137.1 1696.17   143.6 1693.53   150.2 1693.17
   153.4 1693.22   156.7 1693.76   163.2 1695.65   179.5 1699.17   189.3 1699.91
   192.6 1700.46   202.4 1702.41   205.6 1703.41   212.2 1706.43   218.7 1708.84
     235 1713.69   257.9  1721.5   277.5 1730.11   287.3 1734.91   293.8 1737.35
#Mann= 3 ,-1 , 0
       0     .12       0   137.1    .045       0   163.2     .12       0
Bank Sta=137.1,163.2
XS Rating Curve= 0 ,0
Exp/Cntr=0.3,0.1

Type RM Length L Ch R = 1 ,6157    ,163,172,180.8
XS GIS Cut Line= 2
     1986522.128      179119.421     1986512.409      178849.461
#Sta/Elev= 30
       0 1713.21    35.8 1702.91    48.8 1700.35    58.6 1697.51    65.1 1696.13
    81.4 1694.94    91.1 1692.92   100.9 1692.34   126.9 1692.83   133.4 1692.41
   143.2 1690.42   146.5 1690.15   156.2 1690.31   169.2 1692.56   175.8 1693.26
   182.3 1693.17   188.8 1693.57     192 1694.17   195.3 1695.55   198.5 1697.69
   201.8 1700.57     205 1703.98   211.6 1708.41   218.1 1712.24   224.6 1715.48
   234.3 1721.18   244.1 1726.16   250.6 1730.54   257.1 1734.36   270.1 1740.74
#Mann= 3 ,-1 , 0
       0     .12       0   133.4    .045       0   169.2     .12       0
Bank Sta=133.4,169.2
XS Rating Curve= 0 ,0
Exp/Cntr=0.3,0.1

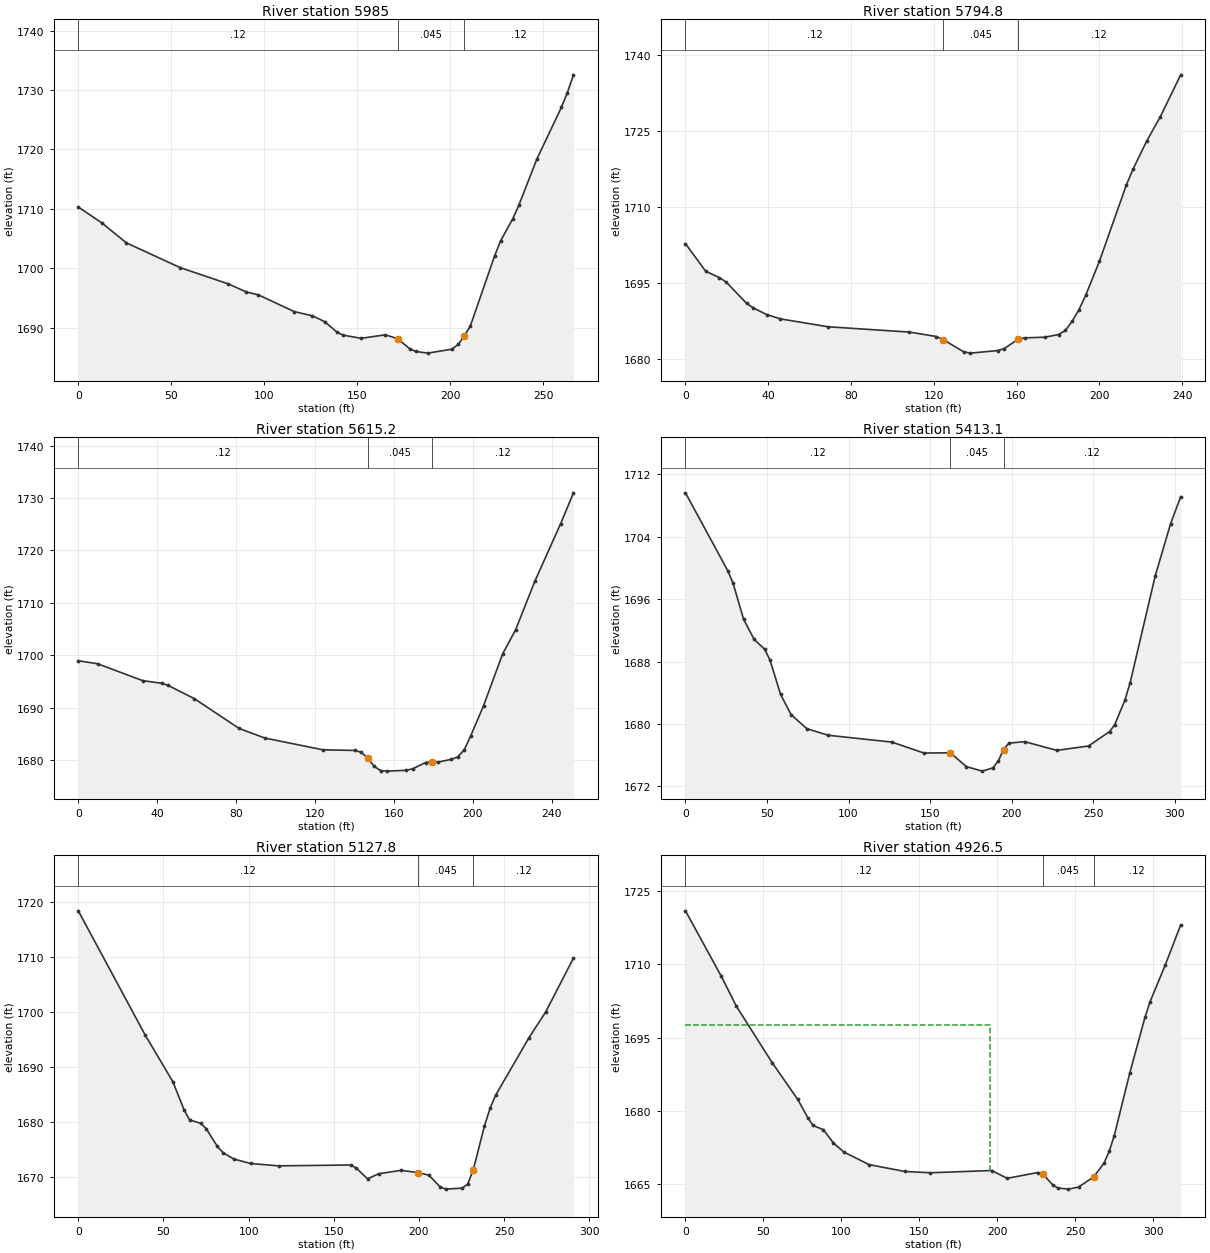
Type RM Length L Ch R = 1 ,5985    ,195.7,190.2,183.5
XS GIS Cut Line= 3
     1986582.939      179120.729     1986674.084      179043.689
     1986701.211      178899.375
#Sta/Elev= 30
       0 1710.32    12.9 1707.58    25.8 1704.29    54.8 1700.11    80.6 1697.38
    90.3 1696.02    96.8 1695.53   116.1 1692.71   125.9    1692   132.4 1691.02
   138.9  1689.3   142.2 1688.76     152 1688.21     165  1688.8   171.6 1688.16
   178.1 1686.48   181.3 1686.01   187.9 1685.72   200.9 1686.39   204.2 1687.18
   207.4 1688.56   210.7 1690.25   223.8 1702.09     227 1704.62   233.6 1708.36
   236.8 1710.61   246.6 1718.45   259.7 1727.09   262.9 1729.57   266.2 1732.57
#Mann= 3 ,-1 , 0
       0     .12       0   171.6    .045       0   207.4     .12       0
Bank Sta=171.6,207.4
XS Rating Curve= 0 ,0
Exp/Cntr=0.3,0.1

Type RM Length L Ch R = 1 ,5794.8  ,192.7,179.6,167
XS GIS Cut Line= 2
     1986864.891      179160.404     1986875.256      178921.336
#Sta/Elev= 30
       0 1702.82     9.8 1697.36    16.4 1696.12    19.7 1695.24    29.5 1691.05
    32.8 1690.14    39.3 1688.83    45.9 1687.98    68.8 1686.43   108.2 1685.38
   121.3  1684.5   124.6 1683.88   134.4  1681.5   137.7 1681.23   150.8 1681.73
   154.1 1682.13   160.6 1683.94   163.9 1684.24   173.7 1684.37   180.3  1684.9
   183.6  1685.7   186.8 1687.48   190.1 1689.75   193.4 1692.62     200  1699.3
   213.1 1714.43   216.4  1717.6   222.9 1723.06   229.5 1727.86   239.3  1736.1
#Mann= 3 ,-1 , 0
       0     .12       0   124.6    .045       0   160.6     .12       0
Bank Sta=124.6,160.6
XS Rating Curve= 0 ,0
Exp/Cntr=0.3,0.1

Type RM Length L Ch R = 1 ,5615.2  ,178,202.2,226.2
XS GIS Cut Line= 2
     1987088.451      179150.547     1987017.921      178909.661
#Sta/Elev= 30
       0 1698.99     9.8 1698.41    32.6  1695.2    42.4 1694.68    45.6 1694.27
    58.7 1691.79    81.5 1686.09    94.5 1684.26   123.9 1682.02   140.2 1681.89
   143.4 1681.53   146.7 1680.43     150 1678.86   153.2 1678.05   156.5 1677.95
   166.2 1678.11   169.5  1678.4     176 1679.59   179.3 1679.74   182.5 1679.68
   189.1  1680.2   192.3 1680.65   195.6    1682   198.8 1684.57   205.4 1690.41
   215.1  1700.3   221.7 1704.91   231.4 1714.13   244.5 1725.12     251 1730.99
#Mann= 3 ,-1 , 0
       0     .12       0   146.7    .045       0   179.3     .12       0
Bank Sta=146.7,179.3
XS Rating Curve= 0 ,0
Exp/Cntr=0.3,0.1

Type RM Length L Ch R = 1 ,5413.1  ,309.3,285.3,260.5
XS GIS Cut Line= 4
     1987216.619      179151.111     1987205.768      179070.816
     1987261.107       178900.46     1987262.192      178857.057
#Sta/Elev= 30
       0 1709.64    25.9 1699.67    29.2 1698.05    35.6 1693.45    42.1 1690.85
    48.6 1689.58    51.9 1688.15    58.3  1683.8    64.8 1681.19    74.5 1679.39
    87.5 1678.56   126.6 1677.68   146.2 1676.28   162.4 1676.31   172.2 1674.54
     182 1673.96   188.5 1674.38   191.8 1675.27     195 1676.73   198.3 1677.55
     208 1677.74   227.6 1676.62   247.1 1677.18   260.1 1679.04   263.2 1679.93
   269.4 1683.05   272.6 1685.27     288 1698.99   297.4 1705.66   303.6 1709.14
#Mann= 3 ,-1 , 0
       0     .12       0   162.4    .045       0     195     .12       0
Bank Sta=162.4,195
XS Rating Curve= 0 ,0
Exp/Cntr=0.3,0.1

Type RM Length L Ch R = 1 ,5127.8  ,200.5,201.3,202
XS GIS Cut Line= 2
     1987535.196      179108.026     1987453.208      178829.149
#Sta/Elev= 30
       0 1718.45    39.2  1695.9    55.5 1687.39    62.1 1682.27    65.3 1680.43
    71.8 1679.83    75.1 1678.83    81.6 1675.63    84.9 1674.49    91.4 1673.31
   101.2 1672.51   117.6 1672.08     160 1672.24   163.3 1671.64   169.8 1669.73
   176.4 1670.65   189.4 1671.26   199.2 1670.87   205.8 1670.39   212.3  1668.3
   215.6 1667.85   225.4 1668.03   228.6 1668.78   231.9 1671.39   238.4  1679.3
   241.7 1682.52     245 1684.92   264.6  1695.4   274.4 1700.07   290.7 1709.87
#Mann= 3 ,-1 , 0
       0     .12       0   199.2    .045       0   231.9     .12       0
Bank Sta=199.2,231.9
XS Rating Curve= 0 ,0
Exp/Cntr=0.3,0.1

Type RM Length L Ch R = 1 ,4926.5  ,223.7,236.5,248.7
XS GIS Cut Line= 2
     1987728.164      179067.474     1987643.529      178761.484
#Sta/Elev= 30
       0 1720.98    22.9 1707.62    32.7 1701.42    55.6  1689.9      72 1682.38
    78.6 1678.56    81.8 1677.05    88.4 1676.19    94.9 1673.45   101.5 1671.62
   117.8 1669.03   140.7 1667.63   157.1 1667.37   196.4 1667.83   206.2 1666.23
   225.8 1667.41   229.1 1667.13   235.6 1664.85   238.9 1664.25   245.5 1664.02
     252 1664.44   261.8 1666.54   268.4 1669.36   271.7 1671.78   274.9 1674.93
   284.8 1687.69   294.6 1699.16   297.8 1702.31   307.7 1709.96   317.5  1718.1
#Mann= 3 ,-1 , 0
       0     .12       0   229.1    .045       0   261.8     .12       0
#XS Ineff= 2 , 0
          195.08 1697.68
Permanent Ineff=
       F       F
Bank Sta=229.1,261.8
XS Rating Curve= 0 ,0
Exp/Cntr=0.3,0.1

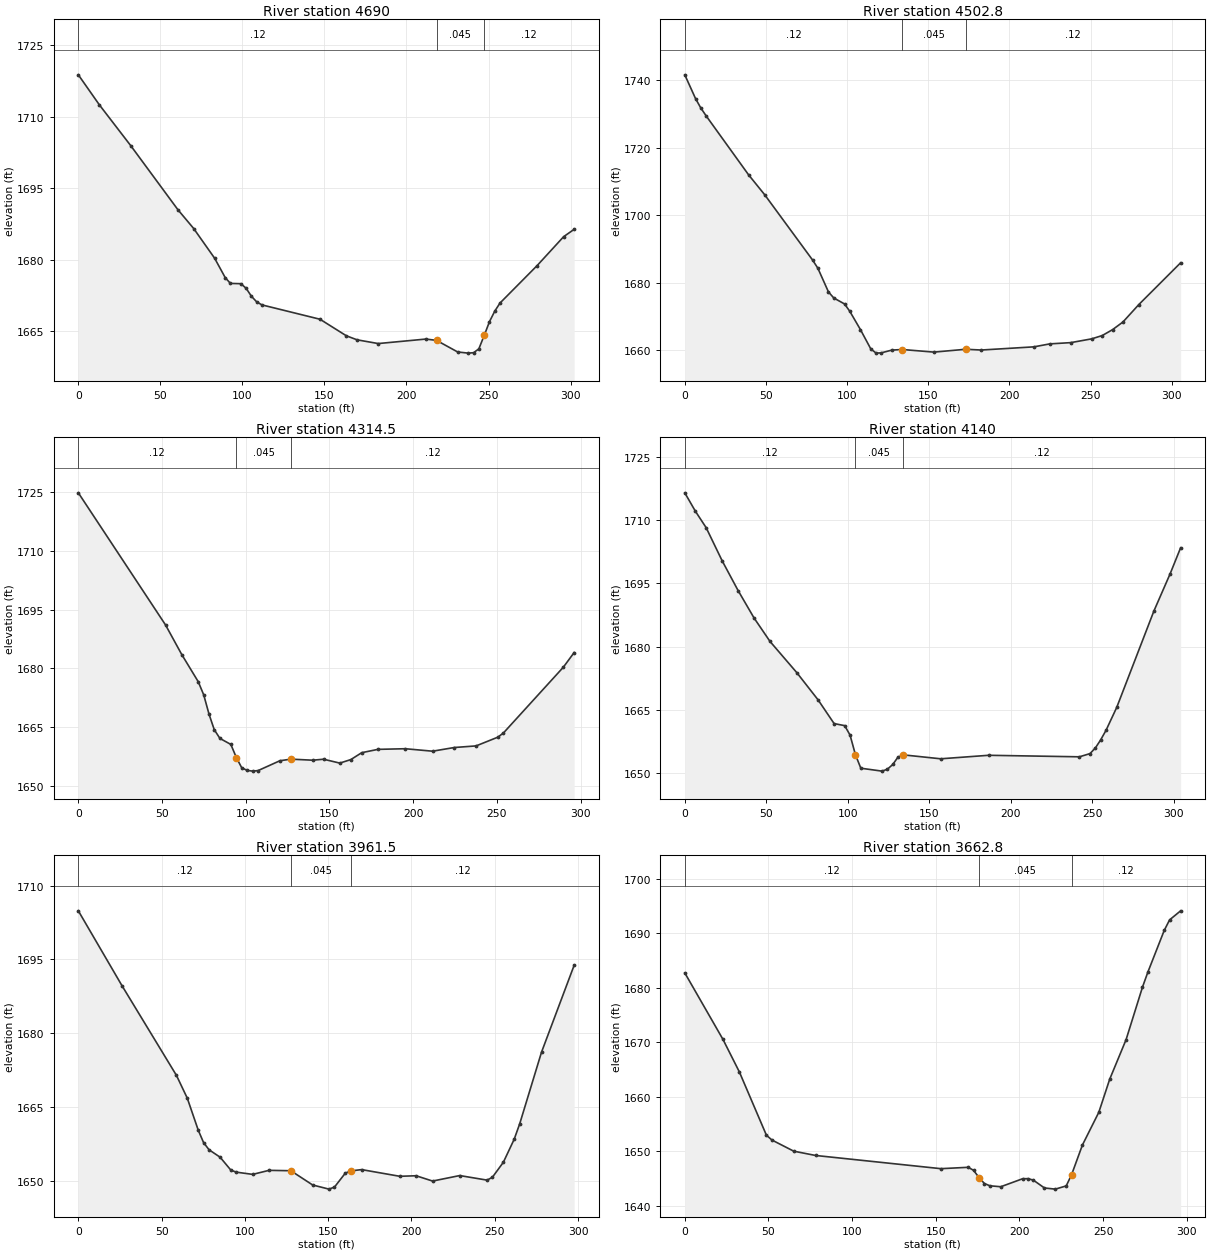
Type RM Length L Ch R = 1 ,4690    ,184.9,187.2,189.3
XS GIS Cut Line= 3
     1987903.251       179041.36     1987885.509      178921.206
     1987892.531      178740.564
#Sta/Elev= 30
       0 1718.83    12.8 1712.54      32 1703.94    60.7 1690.52    70.3 1686.58
    83.1 1680.33    89.5 1676.29    92.7 1675.06    99.1    1675   102.3 1674.02
   105.5 1672.36   108.7 1671.19   111.9 1670.55   147.3 1667.54   163.4 1664.06
   169.9 1663.22   182.8 1662.44   211.8 1663.38   218.3 1663.11   231.2 1660.67
   237.7 1660.43   240.9 1660.52   244.1 1661.32   247.4 1664.16   250.6 1667.04
   253.8 1669.23     257 1670.94   279.6 1678.79   295.8 1684.87   302.2 1686.41
#Mann= 3 ,-1 , 0
       0     .12       0   218.3    .045       0   247.4     .12       0
Bank Sta=218.3,247.4
XS Rating Curve= 0 ,0
Exp/Cntr=0.3,0.1

Type RM Length L Ch R = 1 ,4502.8  ,197.9,188.3,174.9
XS GIS Cut Line= 4
      1988083.59      179014.392     1988064.058       178911.31
     1988075.994      178785.442     1988049.953      178715.998
#Sta/Elev= 30
       0 1741.56     6.6 1734.54     9.8 1731.79    13.1 1729.43    39.3 1711.93
    49.2 1706.04    78.7  1686.7      82 1684.24    88.5 1677.24    91.8 1675.43
    98.4 1673.67   101.6 1671.53   108.2 1666.08   114.6 1660.34   117.9 1659.09
   121.1 1659.18   127.6 1659.99   134.1 1660.16   153.5 1659.39     173 1660.23
   182.7 1660.01   215.1 1660.95   224.9 1661.83   237.8  1662.2   250.7 1663.32
   257.2  1664.3   263.6 1666.06     270 1668.33   279.7 1673.46   305.5 1685.86
#Mann= 3 ,-1 , 0
       0     .12       0   134.1    .045       0     173     .12       0
Bank Sta=134.1,173
XS Rating Curve= 0 ,0
Exp/Cntr=0.3,0.1

Type RM Length L Ch R = 1 ,4314.5  ,177.6,174.5,174.2
XS GIS Cut Line= 2
     1988258.885      178981.964     1988215.968      178688.871
#Sta/Elev= 30
       0 1724.83    52.1 1691.09    61.8 1683.52    71.6 1676.62    74.9 1673.24
    78.1 1668.27    81.2 1664.34    84.6 1662.11    91.1 1660.58    94.4 1657.23
    97.6 1654.62   100.9 1653.94   104.2 1653.76   107.4  1653.9   120.4 1656.41
     127 1656.82     140 1656.55   146.5  1656.8   156.2 1655.81   162.8 1656.71
   169.3 1658.47     179 1659.32   195.3 1659.48   211.6 1658.85   224.6 1659.79
   237.6  1660.2   250.6 1662.43   253.9 1663.48   289.7 1680.28   296.2 1684.05
#Mann= 3 ,-1 , 0
       0     .12       0    94.4    .045       0     127     .12       0
Bank Sta=94.4,127
XS Rating Curve= 0 ,0
Exp/Cntr=0.3,0.1

Type RM Length L Ch R = 1 ,4140    ,176.8,178.5,179.3
XS GIS Cut Line= 2
     1988439.453      178957.059      1988373.39       178660.11
#Sta/Elev= 30
       0 1716.42     6.5 1712.06    13.1 1708.17    22.9 1700.34    32.7 1693.28
    42.5 1686.78    52.3 1681.22    68.7 1673.85    81.8 1667.38    91.6 1661.78
    98.1 1661.29   101.4 1659.04   104.7 1654.39     108 1651.21     121 1650.52
   124.3 1650.97   127.6  1652.1   130.8 1653.84   134.1 1654.37     157 1653.44
   186.4 1654.27   242.1 1653.91   248.6 1654.67   251.9 1656.01   255.1 1657.89
   258.4 1660.16     265 1665.61   287.8 1688.43   297.7 1697.19   304.2 1703.41
#Mann= 3 ,-1 , 0
       0     .12       0   104.7    .045       0   134.1     .12       0
Bank Sta=104.7,134.1
XS Rating Curve= 0 ,0
Exp/Cntr=0.3,0.1

Type RM Length L Ch R = 1 ,3961.5  ,299.1,298.7,263.6
XS GIS Cut Line= 2
     1988610.196      178930.943     1988553.946      178638.582
#Sta/Elev= 30
       0 1704.86    26.2 1689.64    58.9  1671.4    65.4 1666.77      72 1660.25
    75.2 1657.72    78.5 1656.26    85.1 1654.76    91.6 1652.12    94.9 1651.71
   104.7 1651.26   114.5 1652.08   127.6    1652   140.7  1649.1   150.5 1648.26
   153.8 1648.68   160.3 1651.51   163.6 1651.97   170.1 1652.23     193 1650.87
   202.8 1650.98   212.7  1649.9     229 1651.02   245.4 1650.09   248.6 1650.67
   255.2 1653.73   261.7 1658.41     265 1661.54   278.1 1676.11   297.7 1693.79
#Mann= 3 ,-1 , 0
       0     .12       0   127.6    .045       0   163.6     .12       0
Bank Sta=127.6,163.6
XS Rating Curve= 0 ,0
Exp/Cntr=0.3,0.1

Type RM Length L Ch R = 1 ,3662.8  ,258.3,269.9,279.6
XS GIS Cut Line= 2
     1988831.492      178877.818     1988764.218       178589.19
#Sta/Elev= 30
       0 1682.73    22.8 1670.55    32.6 1664.59    48.8 1652.97    52.1 1652.09
    65.1 1650.05    78.2 1649.26   153.1 1646.84   169.4 1647.09   172.6 1646.54
   175.9 1645.21   179.1 1644.12   182.4  1643.7   188.9 1643.53   201.9 1644.99
   205.2 1645.01   208.4 1644.73     215  1643.3   221.5 1643.09     228 1643.68
   231.2 1645.72   237.7 1651.18   247.5 1657.18     254 1663.24   263.8  1670.5
   273.6 1680.12   276.8 1682.86   286.6 1690.52   289.8 1692.45   296.4 1694.11
#Mann= 3 ,-1 , 0
       0     .12       0   175.9    .045       0   231.2     .12       0
Bank Sta=175.9,231.2
XS Rating Curve= 0 ,0
Exp/Cntr=0.3,0.1