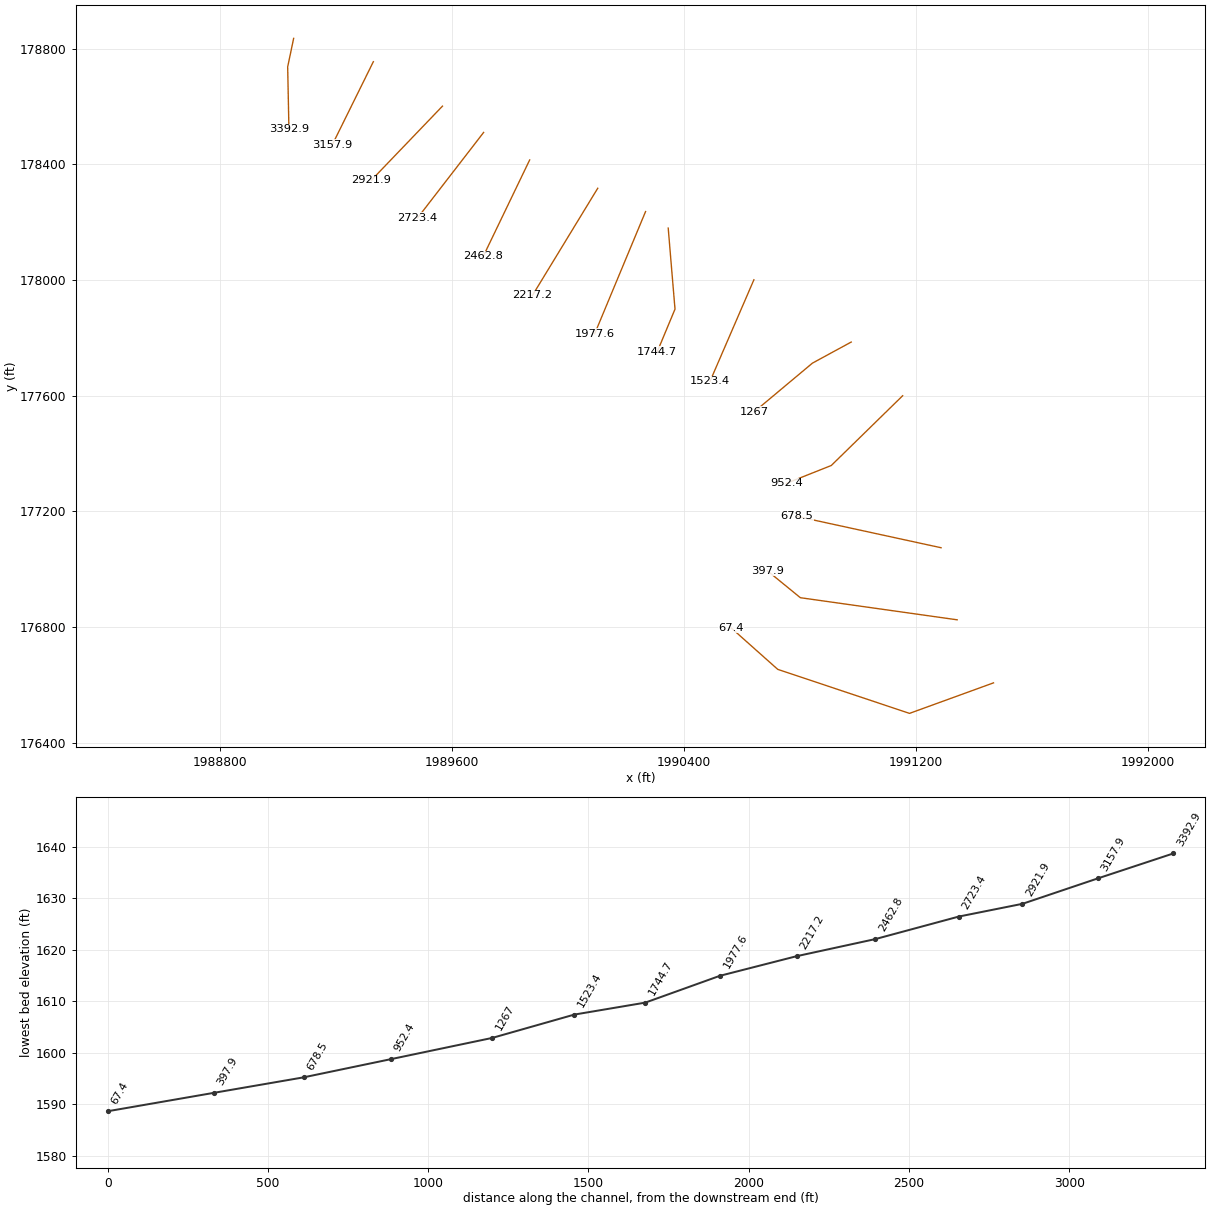
HEC-RAS study DRYFK.prj: DRYFK

--- DRYFK.g01 (geometry) --- (continued)

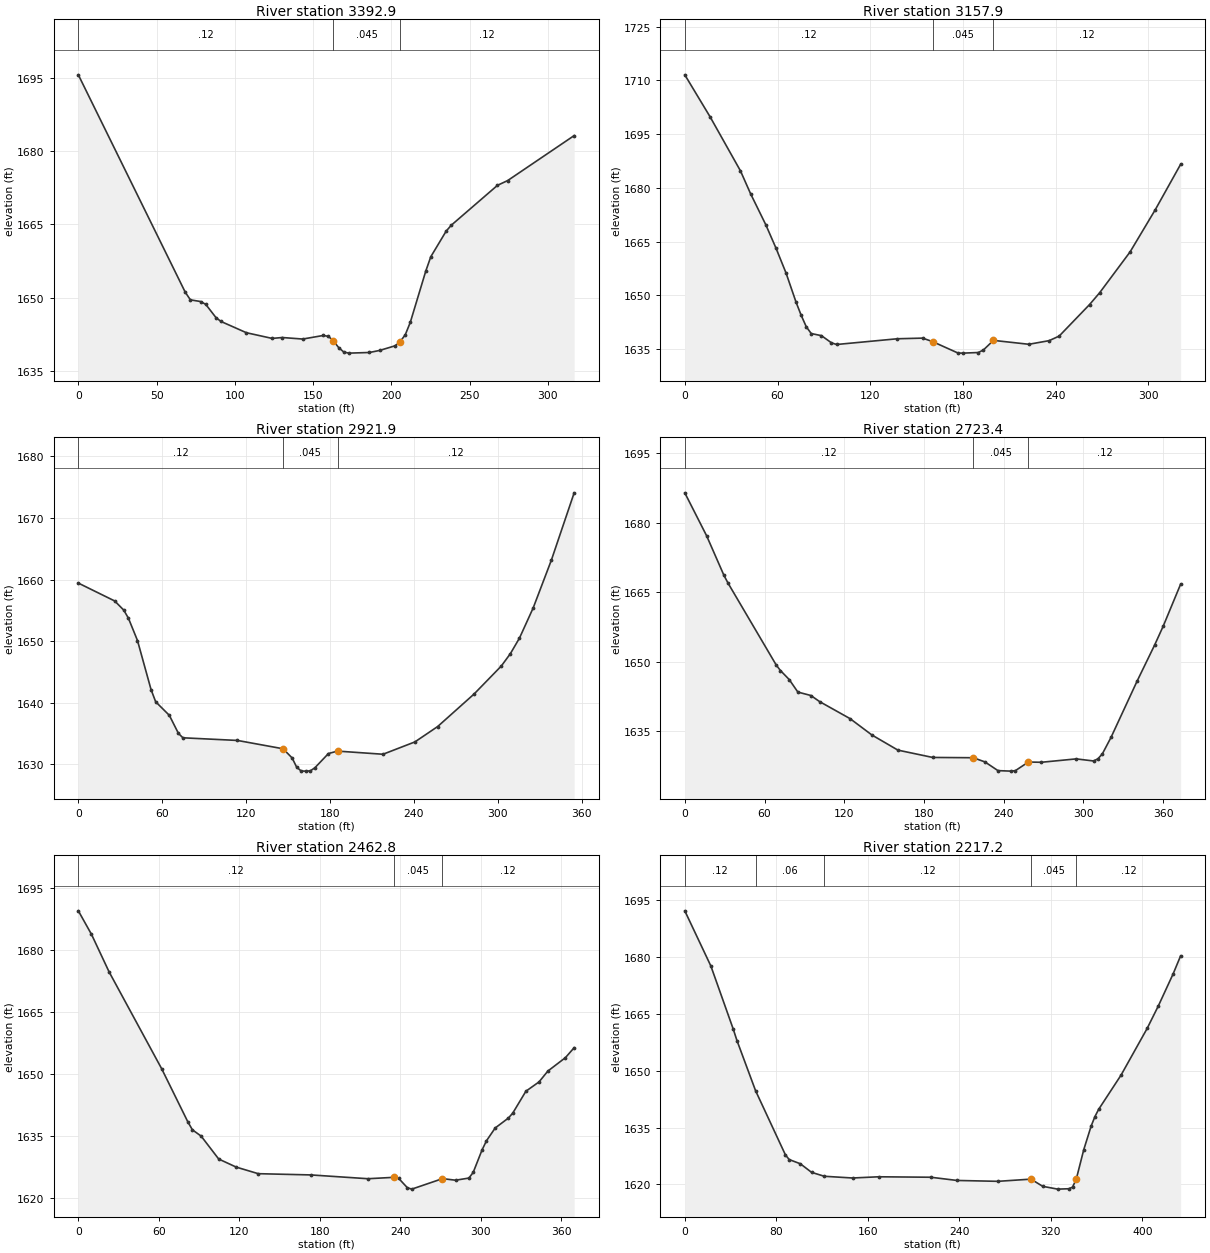
Type RM Length L Ch R = 1 ,3392.9  ,254,235.1,215.9
XS GIS Cut Line= 3
     1989052.687       178835.24     1989032.071      178736.499
     1989036.411       178520.57
#Sta/Elev= 30
       0 1695.57    68.3 1651.14    71.6 1649.57    78.1 1649.23    81.4 1648.65
    87.9 1645.96    91.1 1645.16   107.4 1642.85   123.8 1641.69   130.3 1641.87
   143.4 1641.56   156.5 1642.29   159.8 1642.11     163 1641.17   166.3 1639.83
   169.6  1638.9   172.9 1638.68     186 1638.81   192.5 1639.23   202.3 1640.17
   205.3 1640.89   208.9 1642.44   212.1 1644.97     222 1655.46   225.2 1658.38
     235 1663.61   238.3 1664.83   267.8 1672.98   274.3 1673.95   316.8 1683.15
#Mann= 3 ,-1 , 0
       0     .12       0     163    .045       0   205.3     .12       0
Bank Sta=163,205.3
XS Rating Curve= 0 ,0
Exp/Cntr=0.3,0.1

Type RM Length L Ch R = 1 ,3157.9  ,247.7,236,223.5
XS GIS Cut Line= 2
     1989327.565      178754.521     1989185.659      178466.794
#Sta/Elev= 30
       0 1711.55    16.4  1699.8      36 1684.75    42.6 1678.32    52.4  1669.7
    58.9 1663.27    65.5 1656.22      72 1648.06    75.3 1644.41    78.6 1641.21
    81.8 1639.32    88.4 1638.73    94.9 1636.73    98.2 1636.26   137.5 1637.86
   153.9 1638.04   160.4 1637.05   176.8 1633.87     180 1633.85   189.9 1634.02
   193.2 1634.73   199.7 1637.41   222.6 1636.32   235.7 1637.33   242.2  1638.6
   261.9 1647.42   268.4  1650.7   288.1 1662.11   304.4 1673.89   320.8 1686.57
#Mann= 3 ,-1 , 0
       0     .12       0   160.4    .045       0   199.7     .12       0
Bank Sta=160.4,199.7
XS Rating Curve= 0 ,0
Exp/Cntr=0.3,0.1

Type RM Length L Ch R = 1 ,2921.9  ,192.4,198.5,204.5
XS GIS Cut Line= 2
     1989565.925      178600.865     1989320.699      178344.788
#Sta/Elev= 30
       0 1659.42      26 1656.52    32.5 1655.03    35.8 1653.73    42.3  1650.1
      52 1642.14    55.3 1640.16    65.1 1637.95    71.6 1635.02    74.8 1634.31
   113.8 1633.88   146.4 1632.53   152.9 1631.04   156.1 1629.56   159.4 1628.91
   162.6  1628.9   165.9 1628.94   169.2 1629.45   178.9 1631.76   185.4 1632.15
   217.9 1631.64   240.7 1633.64     257 1636.14     283 1641.41   302.5 1645.96
     309 1647.97   315.5  1650.5   325.3 1655.39   338.3 1663.14   354.6 1674.07
#Mann= 3 ,-1 , 0
       0     .12       0   146.4    .045       0   185.4     .12       0
Bank Sta=146.4,185.4
XS Rating Curve= 0 ,0
Exp/Cntr=0.3,0.1

Type RM Length L Ch R = 1 ,2723.4  ,253.2,260.5,267.3
XS GIS Cut Line= 2
     1989707.852      178509.936     1989479.987      178214.363
#Sta/Elev= 30
       0 1686.45    16.4  1677.2    29.5 1668.63    32.7  1666.9    68.8 1649.32
      72 1648.12    78.6 1646.18    85.1 1643.48    94.9 1642.74   101.5 1641.42
   124.4 1637.75   140.8 1634.23   160.4 1630.96   186.6 1629.38   217.1 1629.32
   225.9 1628.42   235.7 1626.54   245.5 1626.43   248.8 1626.53   258.6 1628.39
   268.4 1628.34   294.6 1629.07   307.7 1628.62     311  1629.1   314.3 1630.16
   320.8  1633.7   340.5 1645.88   353.6  1653.6   360.1  1657.7   373.2 1666.75
#Mann= 3 ,-1 , 0
       0     .12       0   217.1    .045       0   258.6     .12       0
Bank Sta=217.1,258.6
XS Rating Curve= 0 ,0
Exp/Cntr=0.3,0.1

Type RM Length L Ch R = 1 ,2462.8  ,249.6,245.7,241.1
XS GIS Cut Line= 2
     1989866.706      178414.884      1989706.55      178081.551
#Sta/Elev= 30
       0 1689.47     9.8 1683.78    22.9 1674.71    62.2 1651.19    81.8 1638.27
    85.1 1636.42    91.6  1634.9   104.7 1629.35   117.8 1627.39   134.2  1625.8
   173.4  1625.5     216 1624.58   235.6 1624.92   238.9 1624.67   245.4  1622.4
   248.7 1622.06   271.6  1624.6   281.4 1624.22   291.3 1624.74   294.5 1626.11
   301.1 1631.55   304.4 1633.77   310.9 1636.87   320.7 1639.26     324 1640.47
   333.8 1645.77   343.6 1648.03   350.2 1650.66   363.3 1653.91   369.8 1656.32
#Mann= 3 ,-1 , 0
       0     .12       0   235.6    .045       0   271.6     .12       0
Bank Sta=235.6,271.6
XS Rating Curve= 0 ,0
Exp/Cntr=0.3,0.1

Type RM Length L Ch R = 1 ,2217.2  ,233.3,239.6,246.1
XS GIS Cut Line= 2
     1990101.457      178317.054     1989876.186      177946.656
#Sta/Elev= 30
       0 1692.25    22.8 1677.67    42.4 1660.97    45.6 1657.99   61.891644.729
      88 1627.77    91.3 1626.55     101 1625.44   110.8 1623.18  121.961622.135
   146.7 1621.68   169.5    1622   215.1 1621.88     238 1621.03   273.8  1620.8
   302.7 1621.38   312.9 1619.48     326 1618.74   335.7 1618.84     339 1619.26
   342.3 1621.42   348.8 1629.15   355.3 1635.43   358.6 1637.91   361.8  1639.8
   381.4 1648.85   404.2 1661.17     414 1667.12     427 1675.63   433.5 1680.36
#Mann= 5 ,-1 , 0
       0     .12       0   61.89     .06       0  121.96     .12       0
   302.7    .045       0   342.3     .12       0
Bank Sta=302.7,342.3
XS Rating Curve= 0 ,0
Exp/Cntr=0.3,0.1

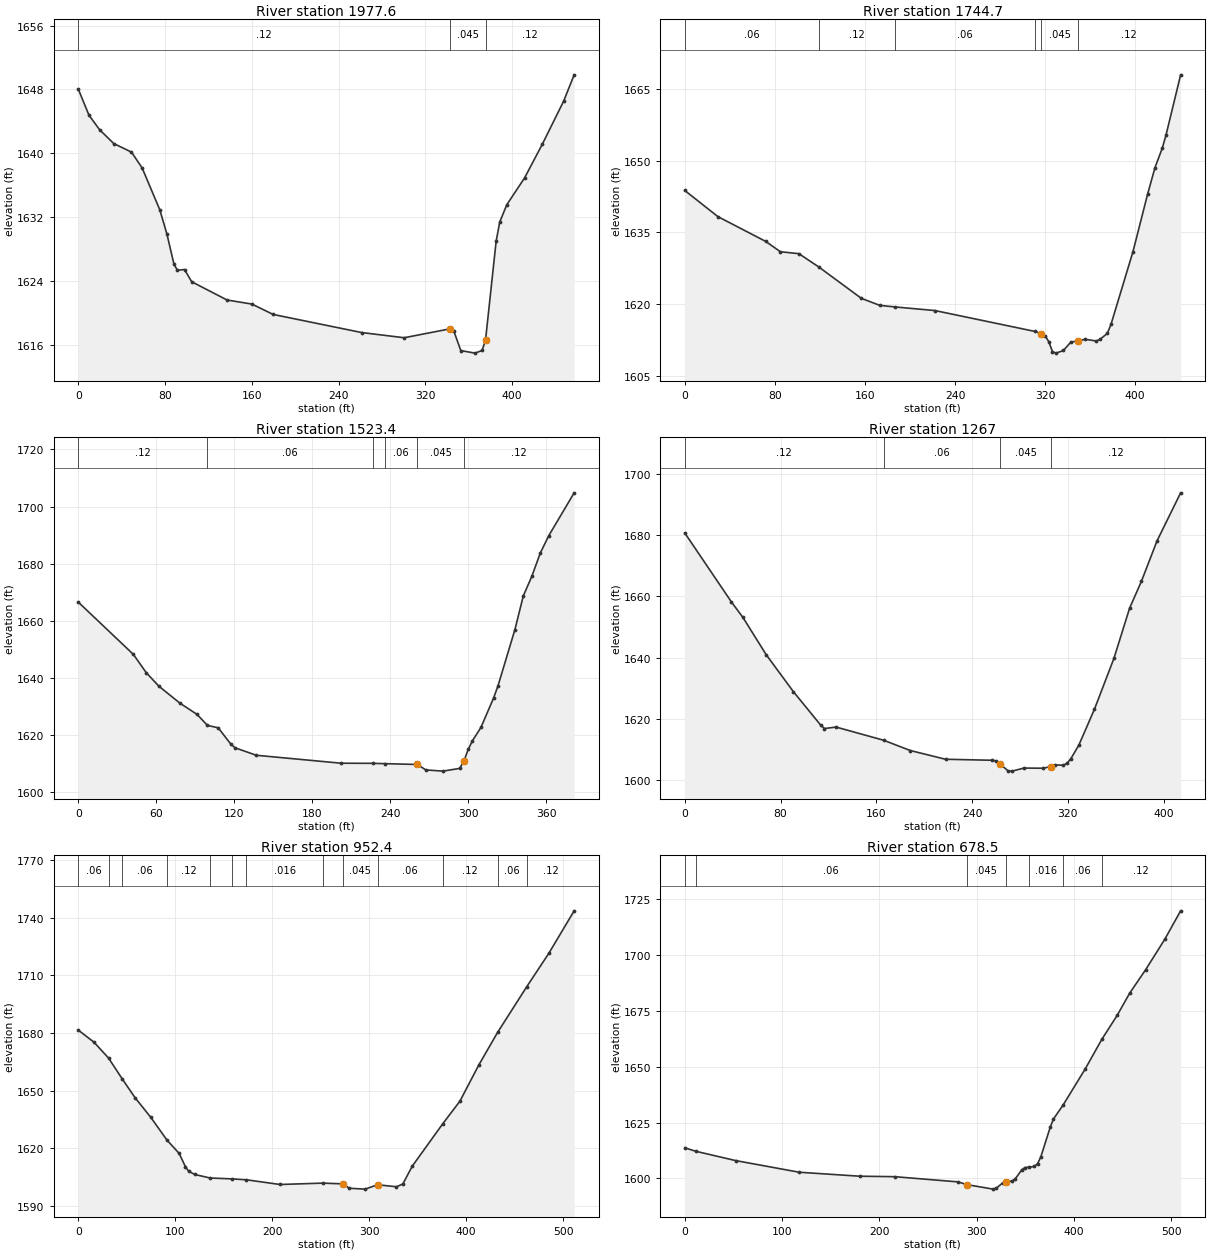
Type RM Length L Ch R = 1 ,1977.6  ,232.4,232.8,232.6
XS GIS Cut Line= 2
     1990266.446      178236.499      1990091.11      177814.394
#Sta/Elev= 30
       0 1648.02     9.8 1644.76    19.6 1642.94    32.6 1641.21      49 1640.13
    58.8 1638.15    75.1  1632.9    81.6 1629.89    88.2 1626.06    91.4 1625.32
    97.9 1625.41   104.5 1623.88   137.1 1621.59     160 1621.08   179.6 1619.78
   261.2 1617.51   300.4 1616.86   342.8 1617.98   346.1 1617.72   352.6 1615.25
   365.7 1614.93   372.2 1615.26   375.4 1616.57   385.2 1628.98   388.5 1631.37
     395 1633.53   411.4  1636.9   427.7 1641.11   447.3 1646.49   457.1 1649.82
#Mann= 3 ,-1 , 0
       0     .12       0   342.8    .045       0   375.4     .12       0
Bank Sta=342.8,375.4
XS Rating Curve= 0 ,0
Exp/Cntr=0.3,0.1

Type RM Length L Ch R = 1 ,1744.7  ,219.4,221.3,222.3
XS GIS Cut Line= 3
     1990344.571      178179.207     1990368.008      177899.259
      1990306.81      177752.124
#Sta/Elev= 30
       0 1643.76    29.4 1638.29    71.9  1633.1    84.9 1630.94   101.3 1630.54
  118.761627.794   156.8 1621.19   173.1 1619.73  186.851619.388   222.1 1618.64
   310.61614.286   316.7 1613.81     320 1613.37   323.2 1612.13   326.5 1610.06
   329.7 1609.73   336.2 1610.28   342.7 1612.01   349.2 1612.34   355.7 1612.62
   365.5 1612.27   368.7 1612.62   375.2 1613.85   378.5 1615.77     398 1630.97
     411 1643.01   417.5 1648.52     424 1652.61   427.3 1655.33   440.3 1667.96
#Mann= 6 ,-1 , 0
       0     .06       0  118.76     .12       0  186.85     .06       0
   310.6     .12       0   316.7    .045       0   349.2     .12       0
Bank Sta=316.7,349.2
XS Rating Curve= 0 ,0
Exp/Cntr=0.3,0.1

Type RM Length L Ch R = 1 ,1523.4  ,274.4,256.4,237.8
XS GIS Cut Line= 2
     1990640.143      178000.821     1990489.102      177650.561
#Sta/Elev= 30
       0 1666.54    42.4 1648.23    52.2 1641.89    61.9 1637.15    78.2 1631.18
    91.3 1627.27   99.341623.411   107.6 1622.57   117.4  1616.8   120.6 1615.57
   136.9 1612.96   202.1 1610.18   226.31610.136  235.631610.025   260.8 1609.74
   267.3 1607.83   280.4 1607.41   293.4 1608.37   296.7 1611.08   299.9 1614.99
   303.2 1618.07   309.7  1622.7   319.5 1633.09   322.8 1637.24   335.8 1656.88
   342.3 1668.76   348.8 1675.53   355.4 1683.78   361.9 1689.83   381.4  1704.8
#Mann= 6 ,-1 , 0
       0     .12       0   99.34     .06       0   226.3     .12       0
  235.63     .06       0   260.8    .045       0   296.7     .12       0
Bank Sta=260.8,296.7
XS Rating Curve= 0 ,0
Exp/Cntr=0.3,0.1

Type RM Length L Ch R = 1 ,1267    ,311.8,314.7,316.4
XS GIS Cut Line= 3
      1990975.78      177785.544     1990841.966      177712.627
     1990641.229      177544.441
#Sta/Elev= 30
       0 1680.76    38.9 1658.24    48.6 1653.12    68.1 1640.91    90.8 1628.84
   113.5 1617.95   116.7 1616.81   126.4 1617.29  166.191612.972   188.4 1609.62
   217.9 1606.76   257.1 1606.43   260.4 1606.21   263.7 1605.13   270.2 1602.95
   273.5 1602.88   283.3 1603.88   299.7 1603.83   305.6 1604.39   309.5 1604.93
   316.1  1604.8   319.3  1605.4   322.6 1606.96   329.2 1611.34   342.3 1623.13
   358.6 1639.78   371.7  1656.2   381.5 1664.92   394.6 1678.19   414.3 1693.89
#Mann= 4 ,-1 , 0
       0     .12       0  166.19     .06       0   263.7    .045       0
   305.6     .12       0
Bank Sta=263.7,305.6
XS Rating Curve= 0 ,0
Exp/Cntr=0.3,0.1

Type RM Length L Ch R = 1 ,952.4   ,314.1,273.9,233.9
XS GIS Cut Line= 3
     1991153.158       177599.98     1990907.071      177358.894
     1990751.906      177297.045
#Sta/Elev= 30
       0 1681.48    16.2 1675.19   31.171666.957   45.081656.271    58.5 1646.34
    74.8 1636.08   91.451624.291     104 1617.36   110.5 1610.42   113.8 1608.11
   120.2 1606.39  136.021604.563  158.331604.114  173.461603.638     208 1601.19
   252.41601.907     273 1601.51   279.5 1599.24   295.8 1598.78   308.8 1601.05
   328.2 1600.01   334.8 1601.48   344.5 1610.75  376.051632.848   393.6 1644.51
   413.3  1663.5  432.591680.364  462.631704.094   485.3 1721.39   511.5 1743.54
#Mann= 13 ,-1 , 0
       0     .06       0   31.17     .12       0   45.08     .06       0
   91.45     .12       0  136.02    .016       0  158.33     .06       0
  173.46    .016       0   252.4     .06       0     273    .045       0
   308.8     .06       0  376.05     .12       0  432.59     .06       0
  462.63     .12       0
Bank Sta=273,308.8
XS Rating Curve= 0 ,0
Exp/Cntr=0.3,0.1

Type RM Length L Ch R = 1 ,678.5   ,276.2,280.6,283.4
XS GIS Cut Line= 2
     1991285.638      177074.654     1990787.713      177183.113
#Sta/Elev= 30
       0 1613.74   11.061612.193    52.3    1608   117.6 1602.79   179.7 1601.01
   215.6  1600.8   280.9 1598.47     290 1597.24   316.9 1595.23   320.1 1595.65
   326.7    1598   329.9 1598.55   336.5 1598.86   339.7 1599.86   346.3 1603.86
   349.5 1604.87   353.6 1605.04   359.3 1605.38   362.6 1606.65   365.9 1609.65
   375.7 1623.08   378.9  1626.6  388.961632.958   411.6 1649.06  428.651662.275
   444.3 1672.93   457.3 1682.96   473.7 1693.44   493.3 1707.02   509.6 1719.76
#Mann= 7 ,-1 , 0
       0     .12       0   11.06     .06       0     290    .045       0
   329.9     .06       0   353.6    .016       0  388.96     .06       0
  428.65     .12       0
Bank Sta=290,329.9
XS Rating Curve= 0 ,0
Exp/Cntr=0.3,0.1

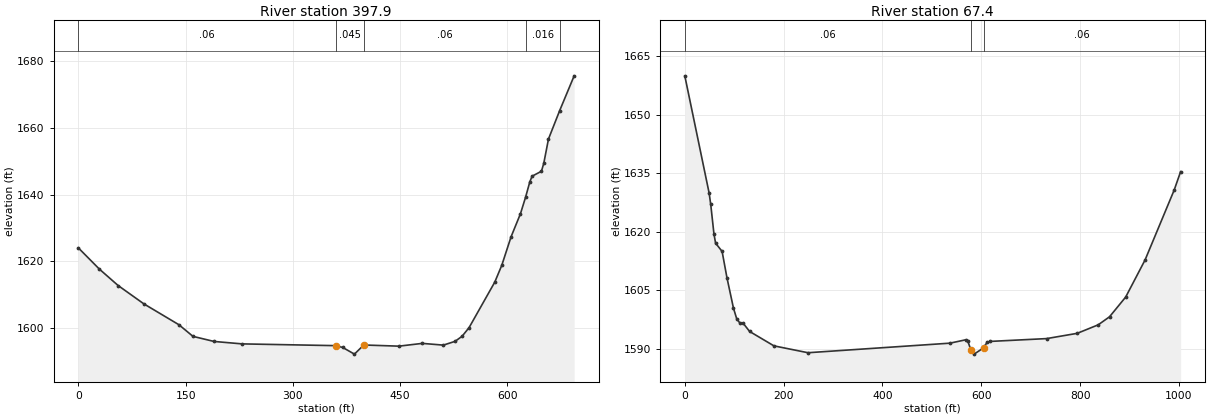
Type RM Length L Ch R = 1 ,397.9   ,336.3,330.2,322.6
XS GIS Cut Line= 3
     1991341.296      176825.528     1990800.373      176901.932
     1990686.669      176994.925
#Sta/Elev= 30
       0 1624.07    29.4 1617.71    55.6 1612.79    91.6 1607.29   140.7 1601.02
   160.3 1597.54   189.7 1596.02     229 1595.29   359.8 1594.76   369.6 1594.22
     386 1592.22   399.1 1594.96   448.2 1594.61   480.9 1595.44   510.3 1594.92
   526.7 1596.05   536.5 1597.57   546.3 1600.17   582.2  1613.8     592 1618.84
     605 1627.39   618.1 1634.29  625.191639.187   631.2 1643.85   634.4 1645.56
   647.5 1647.04   650.8  1649.5   657.3  1656.7  672.981665.236   693.2 1675.64
#Mann= 5 ,-1 , 0
       0     .06       0   359.8    .045       0   399.1     .06       0
  625.19    .016       0  672.98     .06       0
Bank Sta=359.8,399.1
XS Rating Curve= 0 ,0
Exp/Cntr=0.3,0.1

Type RM Length L Ch R = 1 ,67.4    ,57.5,67.3,77.6
XS GIS Cut Line= 4
     1991466.641       176607.63     1991176.858       176502.15
     1990722.392       176654.25     1990561.317      176797.912
#Sta/Elev= 30
       0    1660    49.2 1629.98    52.5 1627.02      59 1619.48    62.3 1617.11
    75.5 1614.99    85.3 1608.26    98.4  1600.5     105 1597.74   111.5 1596.63
   118.1 1596.58   131.2 1594.47   180.4 1590.78   249.3 1589.02   536.6 1591.47
   569.2 1592.35   572.5 1592.08     579 1589.75   585.5 1588.66   605.1  1590.3
   611.6 1591.67   618.1 1591.92   732.2 1592.64   794.2 1593.99   836.7 1596.17
   859.6 1598.23   892.3 1603.29   931.5 1612.79   990.4  1630.7  1003.5 1635.44
#Mann= 3 , 0 , 0
       0     .06       0     579    .045       0   605.1     .06       0
Bank Sta=579,605.1
XS Rating Curve= 0 ,0
Exp/Cntr=0.3,0.1

Chan Stop Cuts=-1
Use User Specified Reach Order=0
Composite Channel Slope=5